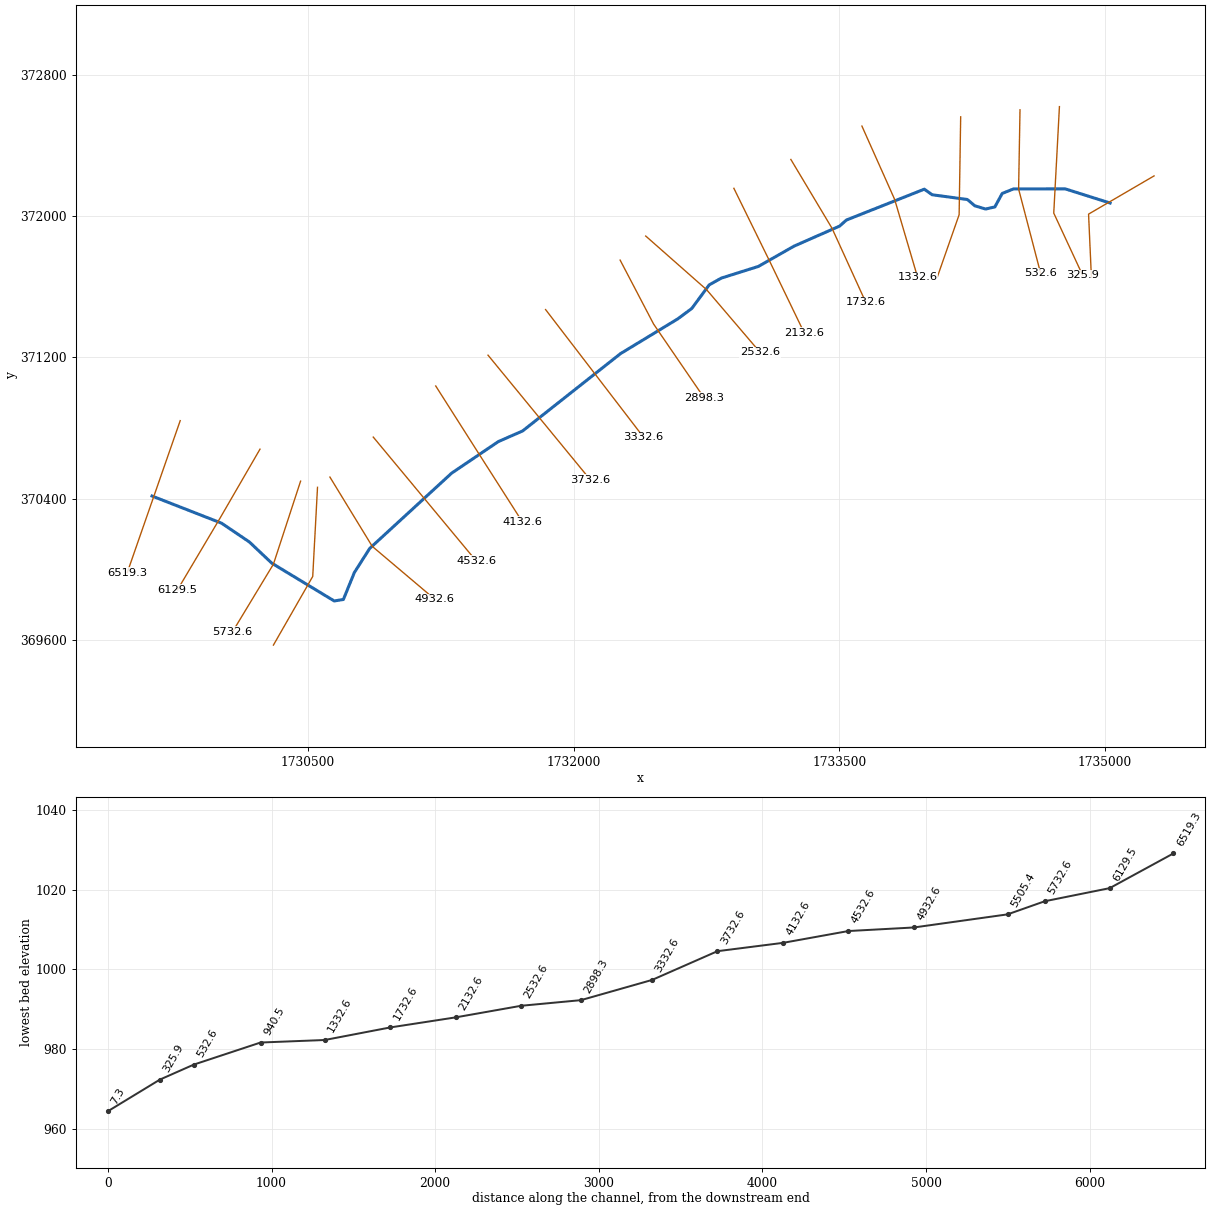
--- FlmngFrk.prj (project) ---

Proj Title=FlmngFrk
Current Plan=p01
Geom File=g01
Flow File=f01
Plan File=p01
DSS Export Rating Curves=0
DSS Export Rating Curve Sorted=0
DSS Export Volume Flow Curves=0
DXF OffsetX=0
DXF OffsetY=0
DXF ScaleX=0
DXF ScaleY=0

--- FlmngFrk.p01 (plan) ---

Plan Title=Floodplain
Program Version=4.00
Geom File=g01
Flow File=f01
K Sum by GR=0
Std Step Tol=0.01
Critical Tol=0.01
Num of Std Step Trials=20
Max Error Tol=0.3
Flow Tol Ratio=0.001
Split Flow NTrial=30
Split Flow Tol=0.02
Split Flow Ratio=0.02
Log Output Level=0
Friction Slope Method=1
Unsteady Friction Slope Method=2
Unsteady Bridges Friction Slope Method=1
Global Log Level=0
CheckData=False
Run HTab=0
Run UNet=0
Run PostProcess=0
UNET Theta=0
UNET Theta Warmup=0
UNET ZTol=0
UNET ZSATol=0
UNET MxIter=0
UNET MaxInSteps=0
UNET DtIC=0
UNET DtMin=0
UNET MaxCRTS=0
UNET WFStab=0
UNET SFStab=0
UNET WFX=0
UNET SFX=0
UNET DSS MLevel=0
UNET DZMax Abort=0
UNET Convert EG Bridges=0
UNET Use Existing IB Tables=0
UNET Froude Limit=0
UNET Froude Power=0
Write IC File=0
Echo Input=False
Echo Output=False
Write Detailed=0

--- FlmngFrk.f01 (steady flow) ---

Flow Title=NFF Regression Equation
Program Version=4.00
Number of Profiles=1
Profile Names=P100yr
River Rch & RM=FlmngFrk,Main      ,6519.3
     722
River Rch & RM=FlmngFrk,Main      ,4932.6
     739
River Rch & RM=FlmngFrk,Main      ,4932.6
    1064
River Rch & RM=FlmngFrk,Main      ,3332.6
    1103
River Rch & RM=FlmngFrk,Main      ,325.9
    1220
River Rch & RM=FlmngFrk,Main      ,7.3
    1220
Boundary for River Rch & Prof#=FlmngFrk,Main      ,1
Up Type=0
Dn Type=3
Dn Slope=0.018835

--- FlmngFrk.g01 (geometry) ---

Geom Title=USGS 3m DEM
Program Version=4.00

River Reach=FlmngFrk     ,Main
Reach XY= 30
     1729620.384      370415.685     1730012.647      370262.227
     1730169.595      370156.009     1730296.413      370035.890
     1730648.684      369822.189     1730700.439      369830.537
     1730762.212      369982.464     1730849.027      370119.366
     1731311.487      370545.096     1731575.273      370723.736
     1731712.175      370783.839     1732264.789      371221.256
     1732588.678      371418.261     1732667.146      371476.694
     1732765.649      371610.257     1732834.099      371648.656
     1733043.003      371714.521     1733244.835      371829.520
     1733501.555      371942.729     1733540.514      371977.234
     1733979.926      372151.649     1734023.995      372120.161
     1734222.947      372093.285     1734265.228      372057.539
     1734325.974      372039.392     1734378.345      372051.426
     1734419.911      372127.736     1734483.281      372153.041
     1734775.227      372153.461     1735028.711      372073.276

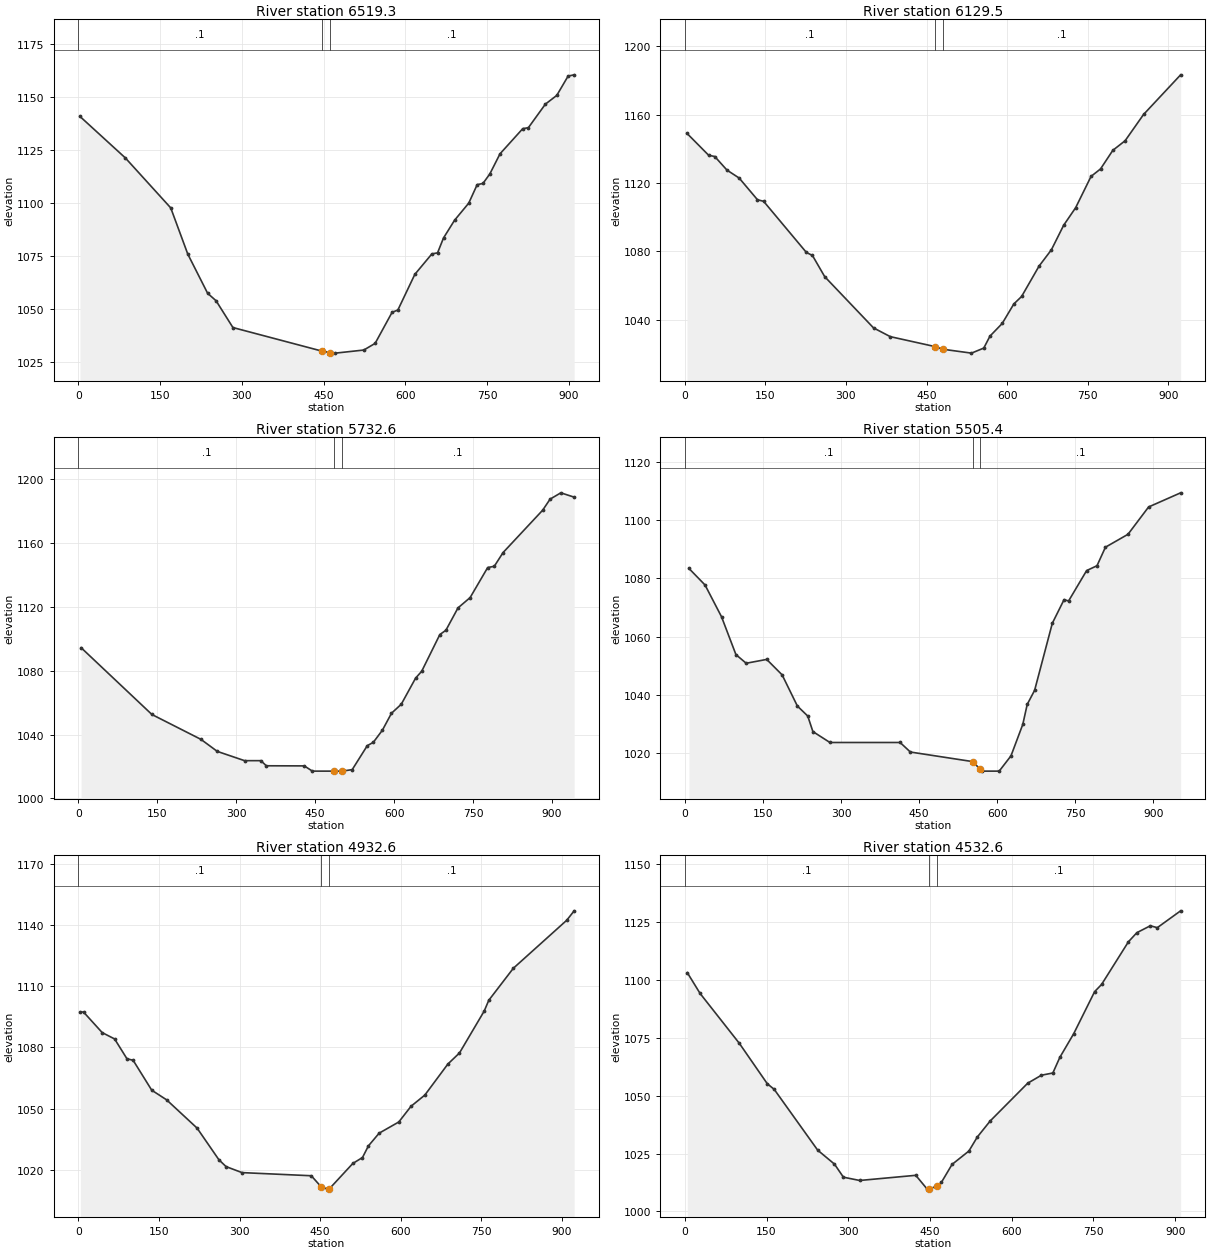
Type RM Length L Ch R = 1 ,6519.3,394.2,389.7,385.2
XS GIS Cut Line= 3
     1729779.281      370842.155     1729629.829      370412.400
     1729480.377      369982.645
#Sta/Elev= 30
     3.0 1140.96    86.3 1121.34   169.6 1097.71   200.9 1075.85   237.3 1057.33
   252.8 1053.80   283.7 1041.13   447.5 1029.96   462.5 1029.23   471.8 1029.03
   523.9 1030.49   544.7 1033.64   575.9 1048.36   586.4 1049.39   617.6 1066.28
   648.9 1075.96   659.3 1076.45   670.2 1083.48   690.5 1091.87   716.6 1099.99
   732.0 1108.71   742.6 1109.27   755.2 1113.75   773.9 1123.28   815.6 1135.17
   826.0 1135.65   857.2 1146.78   878.1 1150.91   898.9 1160.05   910.0 1160.64
#Mann= 3 , 0 , 0
       0     0.1       0   447.5   0.045       0   462.5     0.1       0
Bank Sta=   447.5,   462.5
Exp/Cntr=0.3,0.1

Type RM Length L Ch R = 1 ,6129.5,391.9,396.9,396.8
XS GIS Cut Line= 3
     1730229.789      370681.009     1730003.444      370289.495
     1729763.604      369884.509
#Sta/Elev= 30
     4.0 1149.06    44.4 1136.22    55.8 1135.48    78.5 1127.53   101.2 1122.87
   135.3 1110.16   146.7 1109.25   226.3 1079.31   237.6 1077.53   260.4 1065.13
   351.3 1035.11   382.5 1029.99   465.5 1024.19   480.5 1022.61   533.6 1020.34
   556.5 1023.29   568.0 1030.29   590.8 1037.71   612.5 1049.16   626.9 1053.51
   659.4 1071.31   682.3 1080.82   705.2 1095.23   727.5 1105.50   756.2 1123.85
   773.8 1128.20   796.7 1139.10   819.6 1144.73   853.9 1160.10   922.9 1183.32
#Mann= 3 , 0 , 0
       0     0.1       0   465.5   0.045       0   480.5     0.1       0
Bank Sta=   465.5,   480.5
Exp/Cntr=0.3,0.1

Type RM Length L Ch R = 1 ,5732.6,231.9,227.2,227.8
XS GIS Cut Line= 3
     1730458.873      370499.956     1730305.552      370030.374
     1730074.023      369646.698
#Sta/Elev= 30
     5.3 1094.41   139.8 1052.55   233.0 1036.96   264.0 1029.43   315.8 1023.62
   346.8 1023.62   357.2 1020.41   429.3 1020.34   444.7 1017.06   486.5 1017.06
   501.5 1017.06   520.4 1018.00   549.0 1033.01   560.5 1035.11   577.7 1042.69
   595.0 1053.32   613.6 1058.98   640.9 1075.38   652.4 1079.63   686.9 1102.65
   698.4 1105.34   721.4 1119.35   744.4 1125.80   777.8 1144.64   790.3 1145.42
   807.1 1154.05   882.3 1180.59   896.4 1187.52   916.8 1191.46   942.1 1188.75
#Mann= 3 , 0 , 0
       0     0.1       0   486.5   0.045       0   501.5     0.1       0
Bank Sta=   486.5,   501.5
Exp/Cntr=0.3,0.1

Type RM Length L Ch R = 1 ,5505.4,546.1,572.8,606.2
XS GIS Cut Line= 3
     1730554.417      370465.068     1730527.436      369960.838
     1730305.529      369572.501
#Sta/Elev= 30
     8.0 1083.41    38.9 1077.72    70.5 1066.82    98.2 1053.81   117.9 1050.84
   157.3 1052.16   186.9 1046.85   216.2 1036.14   236.1 1032.71   246.0 1027.37
   278.7 1023.62   413.5 1023.62   433.2 1020.34   552.6 1017.06   567.6 1014.41
   569.8 1013.78   603.8 1013.78   626.4 1019.02   649.1 1029.84   657.6 1036.71
   671.8 1041.54   705.8 1064.58   728.4 1072.71   737.0 1072.22   771.7 1082.68
   791.6 1084.34   807.8 1090.71   851.1 1095.14   890.7 1104.53   952.2 1109.39
#Mann= 3 , 0 , 0
       0     0.1       0   552.6   0.045       0   567.6     0.1       0
Bank Sta=   552.6,   567.6
Exp/Cntr=0.3,0.1

Type RM Length L Ch R = 1 ,4932.6,396.7,400,396
XS GIS Cut Line= 3
     1730624.454      370523.042     1730863.425      370131.064
     1731217.153      369831.356
#Sta/Elev= 30
     3.9 1097.40     9.8 1097.30    44.4 1087.25    67.5 1084.14    90.5 1074.42
   102.0 1073.67   136.6 1059.01   164.3 1054.28   221.0 1040.42   261.6 1024.90
   274.9 1021.55   304.6 1018.60   433.5 1017.06   451.6 1011.73   464.3 1010.50
   466.6 1010.50   510.9 1023.11   528.8 1026.00   539.8 1031.69   559.8 1037.94
   596.4 1043.43   619.1 1051.12   644.8 1056.61   687.7 1071.83   709.3 1077.27
   755.3 1097.81   763.8 1103.09   809.5 1118.79   908.9 1142.34   922.7 1146.96
#Mann= 3 , 0 , 0
       0     0.1       0   451.6   0.045       0   466.6     0.1       0
Bank Sta=   451.6,   466.6
Exp/Cntr=0.3,0.1

Type RM Length L Ch R = 1 ,4532.6,402.9,400,397.2
XS GIS Cut Line= 3
     1730869.162      370749.228     1731159.604      370398.988
     1731450.047      370048.748
#Sta/Elev= 30
     4.6 1103.17    28.1 1094.17   100.2 1072.59   151.4 1055.16   164.1 1052.73
   243.9 1026.45   274.7 1020.42   291.1 1014.77   321.0 1013.35   423.9 1015.58
   444.9 1009.61   447.5 1009.71   462.5 1010.81   470.9 1012.51   490.5 1020.29
   521.4 1026.07   536.8 1032.11   560.4 1039.04   629.3 1055.38   654.5 1058.84
   675.5 1059.80   688.3 1066.55   713.8 1076.80   752.2 1094.97   764.9 1098.06
   814.2 1116.51   829.7 1120.45   854.4 1123.43   867.2 1122.61   910.0 1129.89
#Mann= 3 , 0 , 0
       0     0.1       0   447.5   0.045       0   462.5     0.1       0
Bank Sta=   447.5,   462.5
Exp/Cntr=0.3,0.1

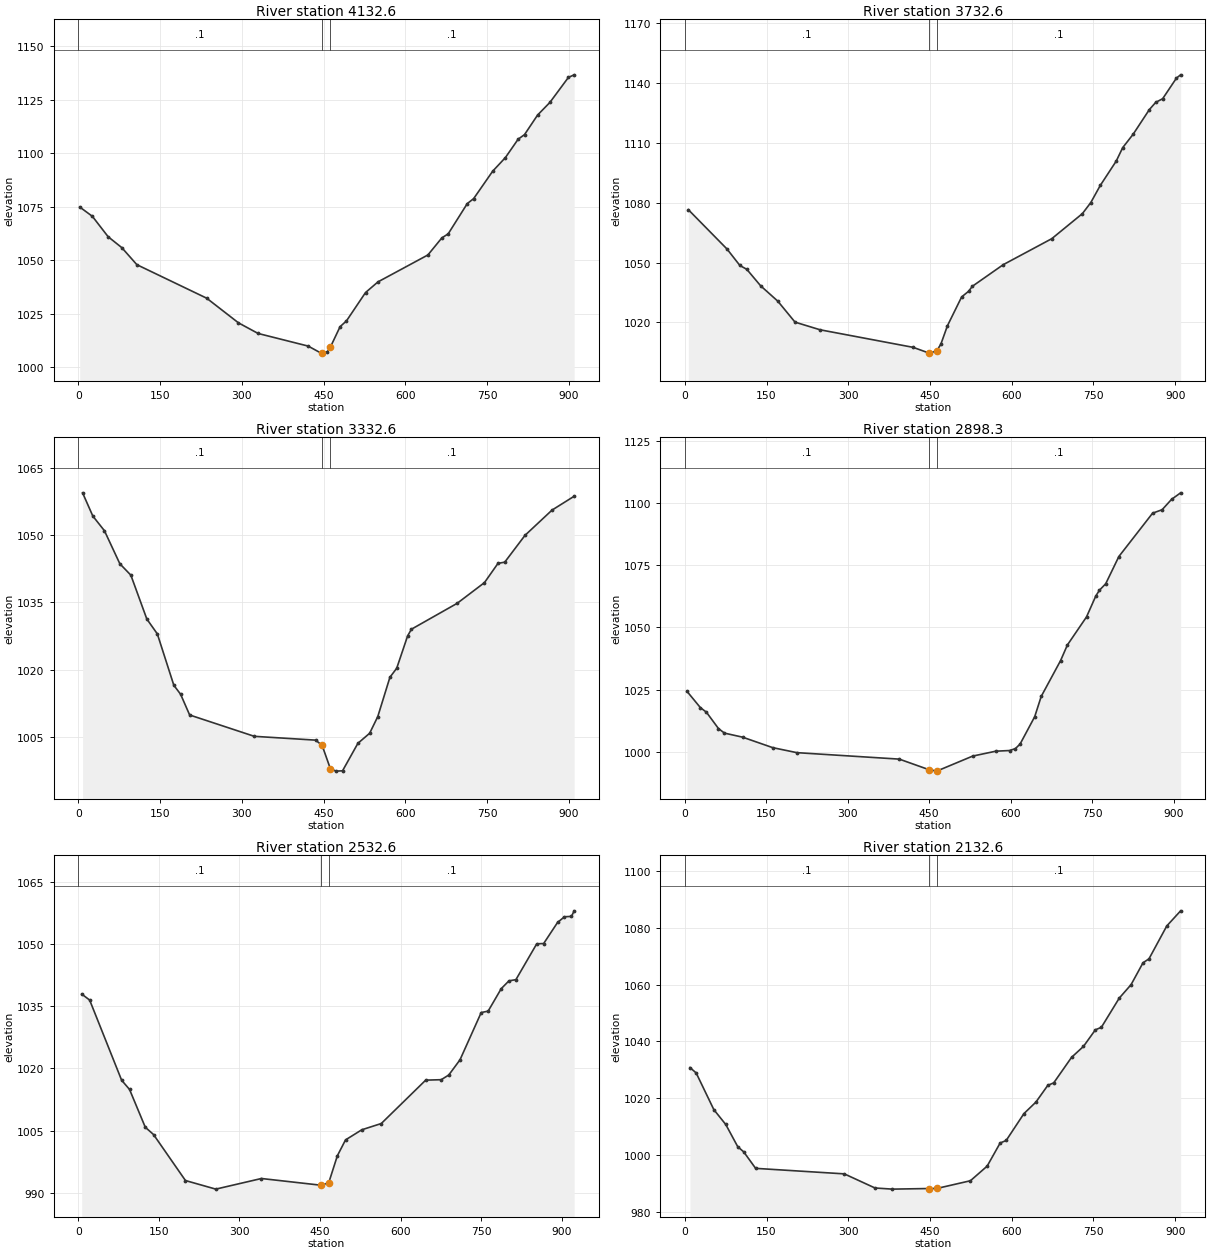
Type RM Length L Ch R = 1 ,4132.6,397.3,400,402.7
XS GIS Cut Line= 3
     1731221.820      371038.261     1731465.763      370654.182
     1731710.330      370270.499
#Sta/Elev= 30
     2.5 1074.90    25.8 1070.53    54.7 1061.01    79.8 1055.91   107.4 1047.96
   235.6 1032.30   293.9 1020.79   330.0 1015.83   421.8 1009.94   445.5 1006.65
   447.5 1006.76   457.1 1007.22   462.5 1009.39   480.4 1019.01   492.1 1021.69
   527.1 1034.94   550.0 1039.93   641.6 1052.50   667.2 1060.47   678.8 1062.35
   713.8 1076.47   725.5 1078.80   760.5 1091.62   783.8 1097.97   807.2 1106.56
   818.9 1108.70   842.9 1117.84   865.5 1123.74   899.5 1135.43   910.0 1136.62
#Mann= 3 , 0 , 0
       0     0.1       0   447.5   0.045       0   462.5     0.1       0
Bank Sta=   447.5,   462.5
Exp/Cntr=0.3,0.1

Type RM Length L Ch R = 1 ,3732.6,400.7,400,399.3
XS GIS Cut Line= 3
     1731516.931      371212.747     1731805.258      370860.763
     1732093.584      370508.779
#Sta/Elev= 30
     6.5 1076.53    77.5 1056.79   101.1 1048.54   113.8 1046.61   139.2 1038.34
   170.7 1030.64   202.3 1020.12   248.3 1016.28   419.1 1007.47   447.5 1004.67
   450.2 1004.57   462.5 1005.83   469.9 1009.01   482.0 1018.29   508.1 1032.77
   520.8 1035.58   527.8 1038.11   584.4 1048.94   673.5 1061.98   729.7 1074.55
   745.2 1080.13   762.5 1088.68   791.8 1100.91   803.7 1107.66   822.9 1114.40
   852.6 1126.75   864.3 1130.38   877.0 1132.20   902.4 1142.57   910.0 1144.19
#Mann= 3 , 0 , 0
       0     0.1       0   447.5   0.045       0   462.5     0.1       0
Bank Sta=   447.5,   462.5
Exp/Cntr=0.3,0.1

Type RM Length L Ch R = 1 ,3332.6,435.5,434.3,433.1
XS GIS Cut Line= 3
     1731841.972      371470.560     1732118.604      371109.312
     1732395.235      370748.064
#Sta/Elev= 30
     7.8 1059.43    26.6 1054.25    47.9 1050.98    76.2 1043.61    96.4 1041.07
   125.7 1031.29   145.0 1027.97   175.3 1016.51   187.7 1014.51   204.3 1009.89
   323.0 1005.13   435.6 1004.28   447.5 1003.09   462.5  997.93   472.8  997.37
   484.9  997.44   513.1 1003.57   534.7 1005.82   549.6 1009.54   571.9 1018.31
   584.3 1020.30   604.4 1027.54   611.4 1029.02   695.3 1034.79   745.4 1039.41
   770.2 1043.70   782.6 1043.97   819.8 1049.95   869.4 1055.58   910.0 1058.67
#Mann= 3 , 0 , 0
       0     0.1       0   447.5   0.045       0   462.5     0.1       0
Bank Sta=   447.5,   462.5
Exp/Cntr=0.3,0.1

Type RM Length L Ch R = 1 ,2898.3,360.1,365.7,368.1
XS GIS Cut Line= 3
     1732262.838      371750.420     1732451.880      371388.357
     1732736.567      370971.790
#Sta/Elev= 30
     4.0 1024.37    28.7 1017.82    39.8 1015.99    62.0 1009.42    73.1 1007.58
   106.4 1005.96   161.9 1001.75   206.3  999.74   395.0  997.14   449.1  992.94
   463.4  992.32   464.1  992.34   530.1  998.36   572.8 1000.33   598.0 1000.59
   608.6 1001.35   617.3 1003.16   644.3 1014.17   656.3 1022.33   692.0 1036.73
   704.5 1042.98   739.7 1054.24   756.8 1062.64   763.5 1064.97   775.0 1067.55
   799.3 1078.51   861.4 1095.91   878.9 1097.29   896.3 1101.46   913.0 1104.08
#Mann= 3 , 0 , 0
       0     0.1       0   449.1   0.045       0   464.1     0.1       0
Bank Sta=   449.1,   464.1
Exp/Cntr=0.3,0.1

Type RM Length L Ch R = 1 ,2532.6,409.1,400,394.1
XS GIS Cut Line= 3
     1732407.388      371886.549     1732751.150      371582.872
     1733052.538      371229.084
#Sta/Elev= 30
     6.3 1037.92    21.1 1036.46    80.6 1017.16    95.4 1014.92   124.7 1005.82
   140.0 1004.07   199.5  992.98   256.0  990.91   341.0  993.47   451.2  991.86
   466.2  992.39   482.4  998.95   497.6 1002.77   527.9 1005.21   564.2 1006.72
   646.9 1017.17   675.9 1017.28   689.9 1018.41   710.8 1022.07   750.3 1033.46
   763.2 1033.80   787.6 1039.22   802.0 1041.10   814.9 1041.38   853.7 1050.02
   866.6 1050.09   892.5 1055.17   905.4 1056.54   918.4 1056.63   923.4 1057.97
#Mann= 3 , 0 , 0
       0     0.1       0   451.2   0.045       0   466.2     0.1       0
Bank Sta=   451.2,   466.2
Exp/Cntr=0.3,0.1

Type RM Length L Ch R = 1 ,2132.6,398.2,400,399.5
XS GIS Cut Line= 3
     1732904.928      372156.614     1733105.032      371747.965
     1733302.449      371338.026
#Sta/Elev= 30
     9.5 1030.79    20.9 1028.88    53.3 1015.98    75.2 1010.75    97.2 1002.93
   108.1 1001.13   130.0  995.32   292.7  993.38   349.1  988.41   381.0  988.01
   447.5  988.22   462.5  988.24   524.2  990.96   554.9  996.10   578.8 1004.25
   589.8 1005.12   622.5 1014.60   644.4 1018.63   666.2 1024.52   677.1 1025.40
   709.9 1034.39   731.7 1038.23   753.6 1044.08   764.5 1044.93   797.3 1055.20
   819.1 1059.97   841.0 1067.66   851.9 1069.03   884.6 1080.61   910.0 1085.93
#Mann= 3 , 0 , 0
       0     0.1       0   447.5   0.045       0   462.5     0.1       0
Bank Sta=   447.5,   462.5
Exp/Cntr=0.3,0.1

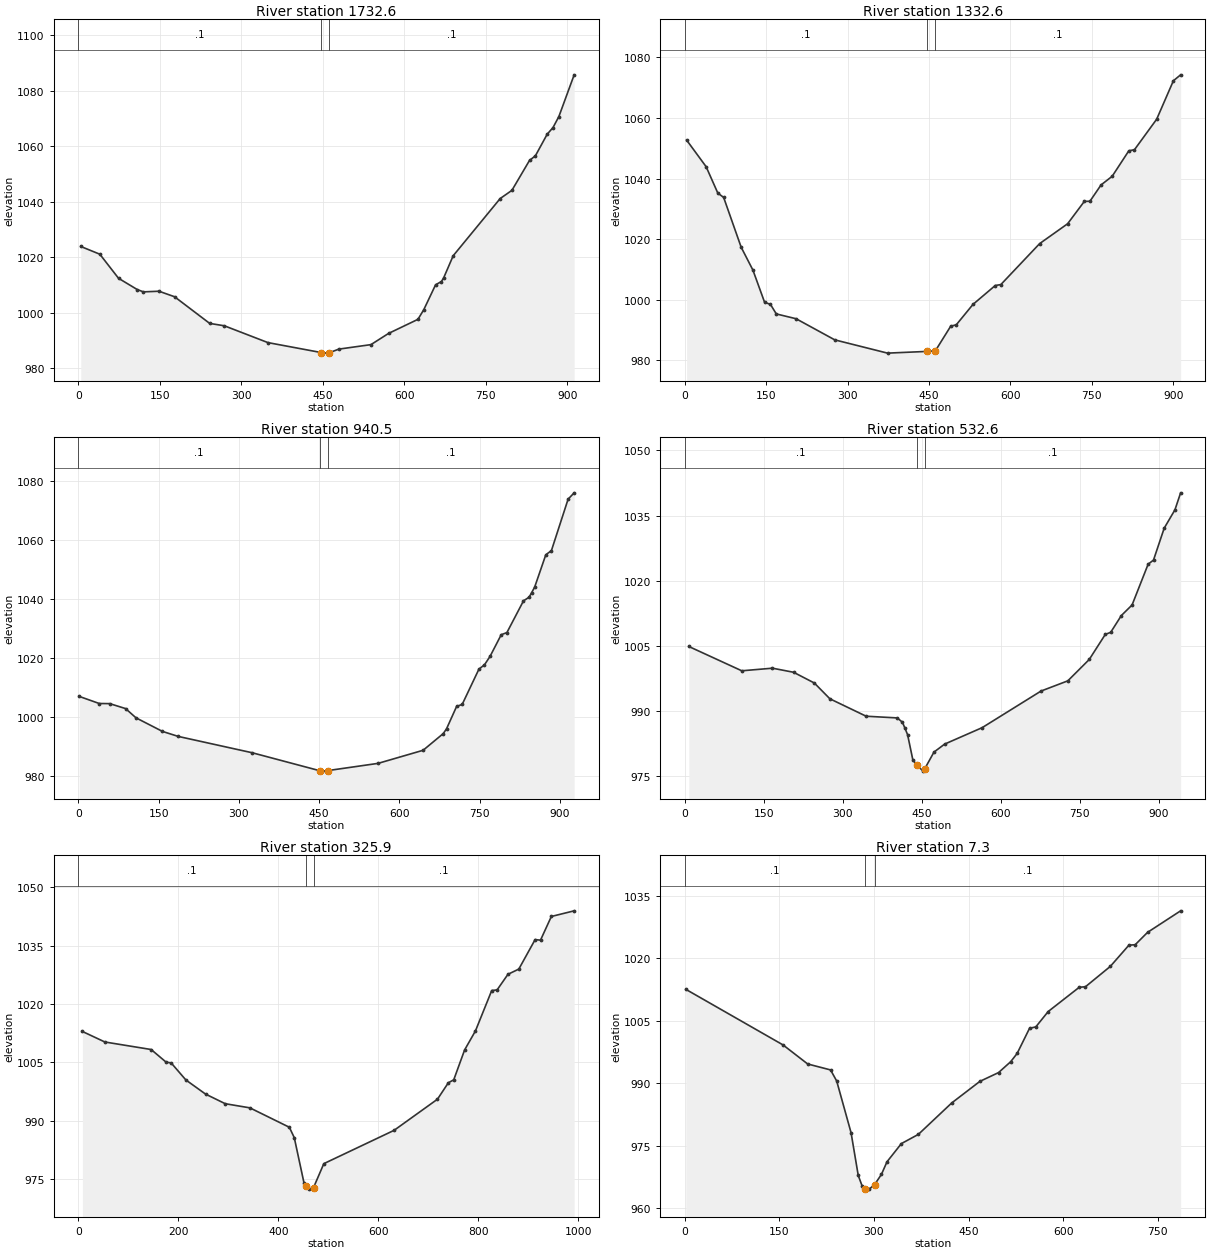
Type RM Length L Ch R = 1 ,1732.6,402.5,400,396.9
XS GIS Cut Line= 3
     1733226.675      372319.892     1733459.536      371929.501
     1733649.314      371512.364
#Sta/Elev= 30
     4.5 1023.88    39.6 1021.09    74.0 1012.43   108.4 1008.38   119.8 1007.54
   148.5 1007.77   177.1 1005.79   241.8  996.19   268.8  995.33   349.0  989.28
   447.1  985.70   459.6  985.49   462.1  985.64   479.5  986.93   538.7  988.55
   571.2  992.59   625.2  997.65   636.0 1001.14   657.7 1010.09   668.5 1011.26
   672.7 1012.64   690.1 1020.54   776.6 1041.13   798.2 1044.08   830.6 1054.85
   841.4 1056.50   863.1 1064.27   873.9 1066.69   884.7 1070.66   912.8 1085.66
#Mann= 3 , 0 , 0
       0     0.1       0   447.1   0.045       0   462.1     0.1       0
Bank Sta=   447.1,   462.1
Exp/Cntr=0.3,0.1

Type RM Length L Ch R = 1 ,1332.6,401.6,392.1,385.1
XS GIS Cut Line= 3
     1733627.744      372508.701     1733812.604      372093.773
     1733942.116      371653.131
#Sta/Elev= 30
     3.3 1052.71    39.3 1043.91    60.8 1035.21    71.6 1033.76   103.9 1017.30
   125.5 1009.77   147.0  999.14   157.8  998.45   168.6  995.29   205.0  993.71
   276.3  986.73   373.5  982.35   446.7  982.92   461.7  983.13   489.9  991.24
   500.2  991.71   531.0  998.45   572.0 1004.68   582.3 1004.99   653.8 1018.52
   705.3 1025.07   736.1 1032.46   746.4 1032.50   766.9 1037.89   787.4 1040.75
   818.1 1049.17   828.4 1049.51   869.4 1059.60   900.2 1072.30   913.5 1074.25
#Mann= 3 , 0 , 0
       0     0.1       0   446.7   0.045       0   461.7     0.1       0
Bank Sta=   446.7,   461.7
Exp/Cntr=0.3,0.1

Type RM Length L Ch R = 1 ,940.5,407.9,407.9,414.3
XS GIS Cut Line= 3
     1734185.298      372561.058     1734176.571      372007.313
     1734053.635      371655.286
#Sta/Elev= 30
     1.5 1007.07    39.1 1004.65    58.7 1004.61    88.3 1002.93   107.8  999.79
   157.2  995.19   186.7  993.49   324.5  987.97   451.2  981.86   462.2  981.72
   466.2  981.90   560.2  984.35   644.4  988.79   682.1  994.46   688.3  996.12
   707.0 1003.66   717.4 1004.33   748.7 1016.30   759.1 1017.78   769.5 1020.63
   790.4 1027.98   801.0 1028.70   832.0 1039.46   842.5 1040.70   847.3 1042.25
   852.9 1044.13   873.7 1055.08   884.2 1056.50   915.4 1073.95   926.7 1076.09
#Mann= 3 , 0 , 0
       0     0.1       0   451.2   0.045       0   466.2     0.1       0
Bank Sta=   451.2,   466.2
Exp/Cntr=0.3,0.1

Type RM Length L Ch R = 1 ,532.6,207.5,206.7,199.6
XS GIS Cut Line= 3
     1734520.251      372600.677     1734512.316      372152.527
     1734636.928      371675.102
#Sta/Elev= 30
     7.7 1004.87   108.2  999.28   166.5  999.88   206.6  998.94   246.0  996.47
   275.5  992.84   344.4  988.83   403.5  988.44   413.3  987.44   418.0  986.10
   423.1  984.58   433.0  978.83   440.7  977.54   452.8  976.20   455.7  976.75
   473.2  980.58   493.5  982.42   564.7  986.20   676.5  994.62   727.4  996.97
   768.1 1001.89   798.6 1007.66   808.8 1008.13   829.1 1012.00   849.4 1014.42
   879.9 1023.80   890.1 1024.75   910.4 1032.09   930.8 1036.31   941.6 1040.22
#Mann= 3 , 0 , 0
       0     0.1       0   440.7   0.045       0   455.7     0.1       0
Bank Sta=   440.7,   455.7
Exp/Cntr=0.3,0.1

Type RM Length L Ch R = 1 ,325.9,341,318.5,295.9
XS GIS Cut Line= 3
     1734742.812      372618.731     1734710.771      372016.360
     1734874.180      371663.909
#Sta/Elev= 30
     8.2 1012.94    53.1 1010.24   145.6 1008.31   175.7 1005.05   185.6 1004.88
   215.1 1000.49   254.5  996.86   293.9  994.39   343.1  993.33   422.0  988.35
   431.9  985.68   451.6  973.91   455.4  973.36   461.5  972.46   470.4  972.84
   491.0  979.00   631.6  987.56   718.3  995.55   740.0  999.76   750.9 1000.54
   772.6 1008.20   794.3 1013.09   826.8 1023.45   837.6 1023.62   859.3 1027.62
   881.0 1028.96   913.6 1036.53   924.4 1036.39   946.1 1042.47   991.7 1043.92
#Mann= 3 , 0 , 0
       0     0.1       0   455.4   0.045       0   470.4     0.1       0
Bank Sta=   455.4,   470.4
Exp/Cntr=0.3,0.1

Type RM Length L Ch R = 1 ,7.3,2.7,7.3,12.2
XS GIS Cut Line= 3
     1735277.087      372226.774     1734907.283      372010.581
     1734923.263      371652.893
#Sta/Elev= 30
     1.6 1012.54   155.9  999.17   194.9  994.60   231.2  993.17   240.9  990.51
   263.7  978.09   275.1  967.81   281.5  965.19   285.9  964.63   292.4  964.53
   300.9  965.59   311.9  968.08   320.7  971.10   343.5  975.47   370.4  977.68
   423.3  985.23   468.0  990.42   497.6  992.53   516.9  995.15   527.1  997.13
   546.8 1003.18   556.7 1003.51   576.4 1007.21   625.6 1013.03   635.5 1013.16
   674.9 1018.05   704.4 1023.15   714.3 1023.25   734.0 1026.23   786.4 1031.40
#Mann= 3 , 0 , 0
       0     0.1       0   285.9   0.045       0   300.9     0.1       0
Bank Sta=   285.9,   300.9
Exp/Cntr=0.3,0.1